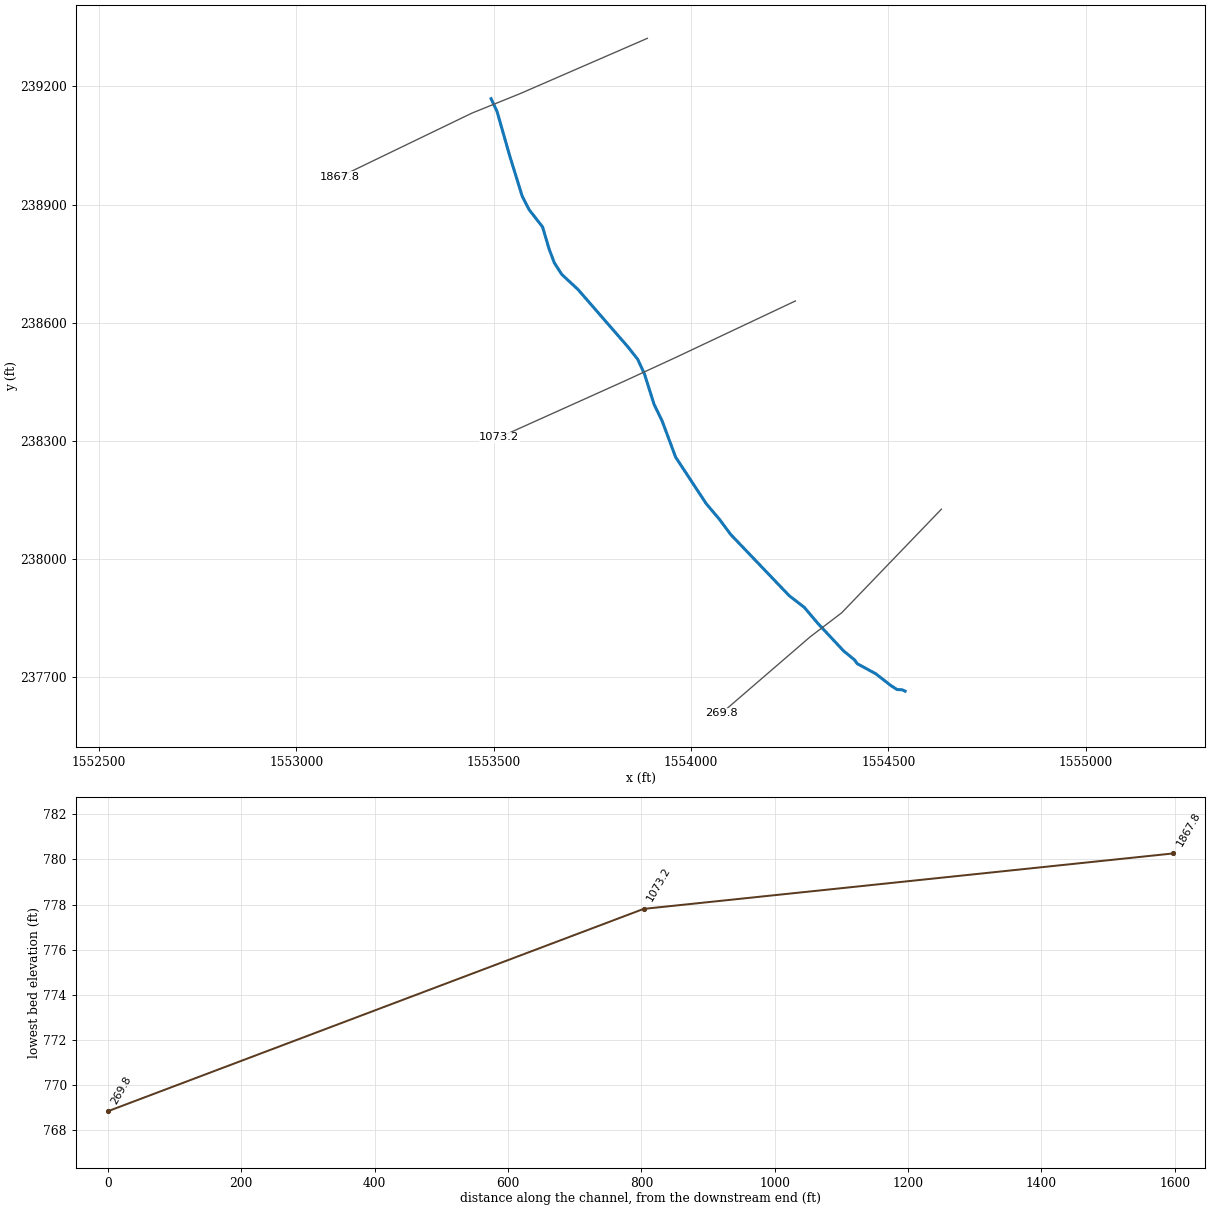
--- ISCFR.prj (project) ---

Proj Title=ISCFR
Current Plan=p01
Default Exp/Contr=0,0
English Units
Geom File=g01
Flow File=f01
Plan File=p01
BEGIN DESCRIPTION:
END DESCRIPTION:
DSS Export Rating Curves= 0
DSS Export Rating Curve Sorted= 0
DSS Export Volume Flow Curves= 0
DXF OffsetX= 0
DXF OffsetY= 0
DXF ScaleX= 0
DXF ScaleY= 0

--- ISCFR.p01 (plan) ---

Plan Title=Floodplain
Program Version=4.00
Geom File=g01
Flow File=f01
K Sum by GR=0
Std Step Tol=0.01
Critical Tol=0.01
Num of Std Step Trials=20
Max Error Tol=0.3
Flow Tol Ratio=0.001
Split Flow NTrial=30
Split Flow Tol=0.02
Split Flow Ratio=0.02
Log Output Level=0
Friction Slope Method=1
Unsteady Friction Slope Method=2
Unsteady Bridges Friction Slope Method=1
Global Log Level=0
CheckData=False
Run HTab=0
Run UNet=0
Run PostProcess=0
UNET Theta=0
UNET Theta Warmup=0
UNET ZTol=0
UNET ZSATol=0
UNET MxIter=0
UNET MaxInSteps=0
UNET DtIC=0
UNET DtMin=0
UNET MaxCRTS=0
UNET WFStab=0
UNET SFStab=0
UNET WFX=0
UNET SFX=0
UNET DSS MLevel=0
UNET DZMax Abort=0
UNET Convert EG Bridges=0
UNET Use Existing IB Tables=0
UNET Froude Limit=0
UNET Froude Power=0
Write IC File=0
Echo Input=False
Echo Output=False
Write Detailed=0

--- ISCFR.f01 (steady flow) ---

Flow Title=NFF Regression Equation
Program Version=4.10
Number of Profiles= 1
Profile Names=P100yr
River Rch & RM=ISCFR,Main            ,1867.8
896.0176
River Rch & RM=ISCFR,Main            ,269.8
 916.078
Boundary for River Rch & Prof#=ISCFR,Main            , 1
Up Type= 0
Dn Type= 3
Dn Slope=0.0112
DSS Import GetInterval= 0
DSS Import GetPeak= 0
DSS Import FillOption= 0

--- ISCFR.g01 (geometry) ---

Geom Title=USGS 10m DEM
Program Version=4.10

River Reach=ISCFR           ,Main
Reach XY= 30
     1553493.621      239168.679     1553508.904       239135.72
      1553540.16      239025.781       1553572.5      238921.015
      1553590.06      238886.837      1553624.06       238843.11
     1553640.555      238787.332     1553653.771      238752.127
     1553672.692      238722.629     1553713.585      238684.591
     1553840.263      238538.657      1553865.14      238507.048
     1553882.177      238469.888     1553906.596      238392.546
     1553926.979      238350.568     1553961.101       238258.78
     1554038.497      238140.763     1554072.321      238100.704
     1554100.564      238062.506     1554249.058      237906.877
     1554287.003      237877.498     1554320.967      237837.253
     1554386.587      237766.937     1554414.213      237744.197
     1554421.181      237734.493      1554467.98      237708.966
     1554506.878      237678.576     1554522.073      237668.852
     1554534.796      237668.301     1554542.524      237664.752

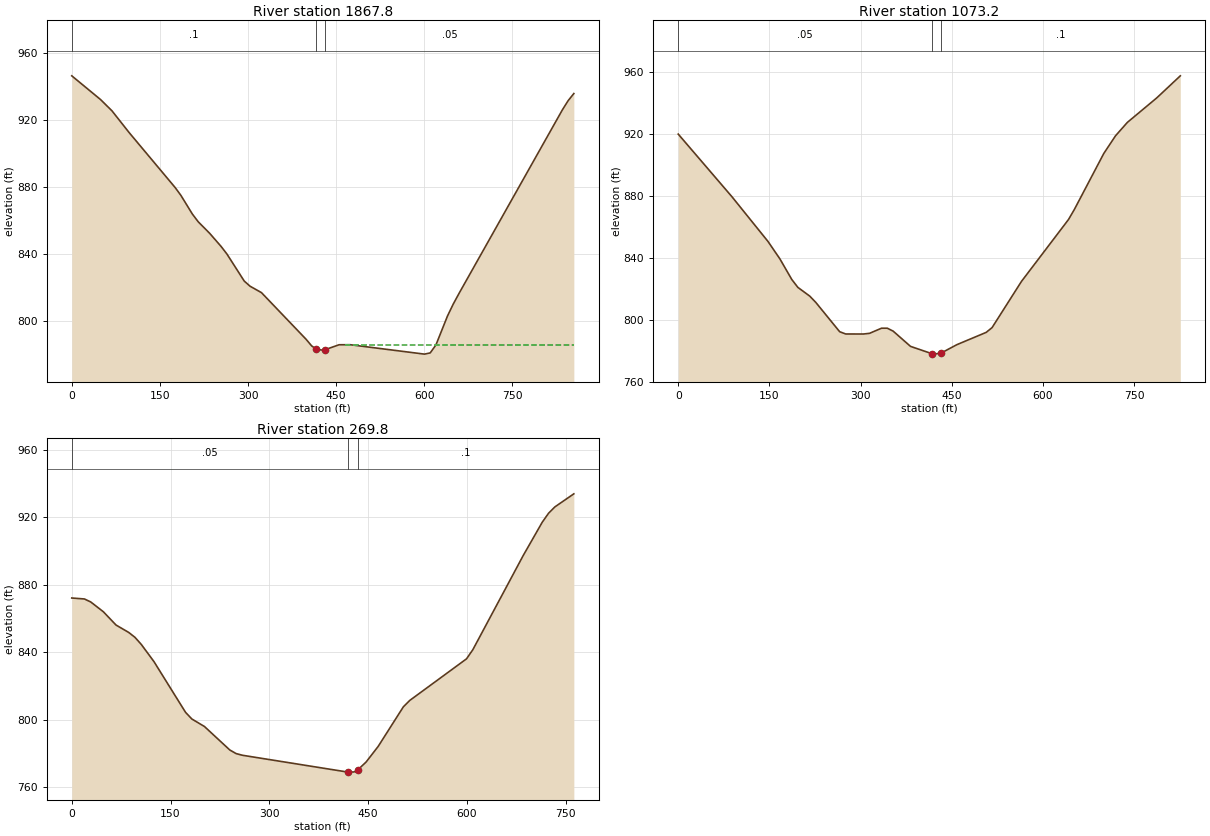
Type RM Length L Ch R = 1 ,1867.8  ,793.4,794.5,795.5
XS GIS Cut Line= 4
     1553889.495      239321.873     1553566.578      239181.248
     1553445.354      239132.136     1553110.849      238970.311
#Sta/Elev= 30
       0  946.12    48.9  932.01    68.5  925.23    97.8  912.24   176.1  879.49
   185.9   874.8   205.4  863.69   215.2  859.16   234.8  852.24   254.4  844.35
   264.2  839.88   293.5  823.85   303.3  820.78   322.9  816.92   398.9   789.1
   408.3  785.18   416.2  783.28     427  782.58   431.2  782.93     455  785.85
   473.7  785.88   600.4  780.27   610.1  780.99   619.9  785.77   639.5  802.96
   649.2  810.01     659  816.35     835  925.79   844.8  931.27   854.6  935.56
#Mann= 3 , 0 , 0
       0      .1       0   416.2    .045       0   431.2     .05       0
#XS Ineff= 2 , 0
                          464.54          785.89
Permanent Ineff=
       F       F
Bank Sta=416.2,431.2
XS Rating Curve= 0 ,0
Exp/Cntr=0.3,0.1

Type RM Length L Ch R = 1 ,1073.2  ,798.4,803.4,808.3
XS GIS Cut Line= 4
     1554264.495      238655.206     1553962.109      238512.165
     1553832.203      238452.081     1553514.495      238308.852
#Sta/Elev= 30
       0  919.83    88.6   879.3   147.6  850.58   167.3  839.28   186.9  825.96
   196.8  820.92   216.4  815.25   226.3  811.22   265.6  792.29   275.5  790.81
     305   790.8   314.8  791.24   334.5  794.54     344  794.55   353.6  792.66
   382.2  782.81   417.3  778.11   420.4  777.81   432.3  778.46   458.6  783.94
   506.7  791.85   516.4  794.93   564.8  824.78   642.2  864.73   651.9  871.28
   700.3   907.4   719.6  918.79     739  927.39   787.4  943.22   826.1  957.45
#Mann= 3 , 0 , 0
       0     .05       0   417.3    .045       0   432.3      .1       0
Bank Sta=417.3,432.3
XS Rating Curve= 0 ,0
Exp/Cntr=0.3,0.1

Type RM Length L Ch R = 1 ,269.8   ,252.7,269.8,285.8
XS GIS Cut Line= 4
     1554634.287      238126.561     1554381.682       237863.54
     1554301.816      237802.533     1554076.995      237608.331
#Sta/Elev= 30
       0   872.1    19.2  871.53    28.8  869.76      48  863.93    67.2  856.07
    86.4   851.7      96  848.76   105.6  844.55   124.8  834.38   172.7  804.33
   182.3  800.36   201.5  795.88   239.9  781.98   249.5  779.84   259.1  778.84
   419.5  768.84   419.8  768.84   428.6  768.94   434.8  770.38   446.9  774.84
   465.2  784.08   503.5  807.59   513.1  811.34   599.3  836.01   608.9  841.41
   685.6  897.41   714.3  917.01   723.9  922.36   733.5  926.12   762.3  933.88
#Mann= 3 , 0 , 0
       0     .05       0   419.8    .045       0   434.8      .1       0
Bank Sta=419.8,434.8
XS Rating Curve= 0 ,0
Exp/Cntr=0.3,0.1

Chan Stop Cuts=-1
Use User Specified Reach Order=0
Composite Channel Slope=5